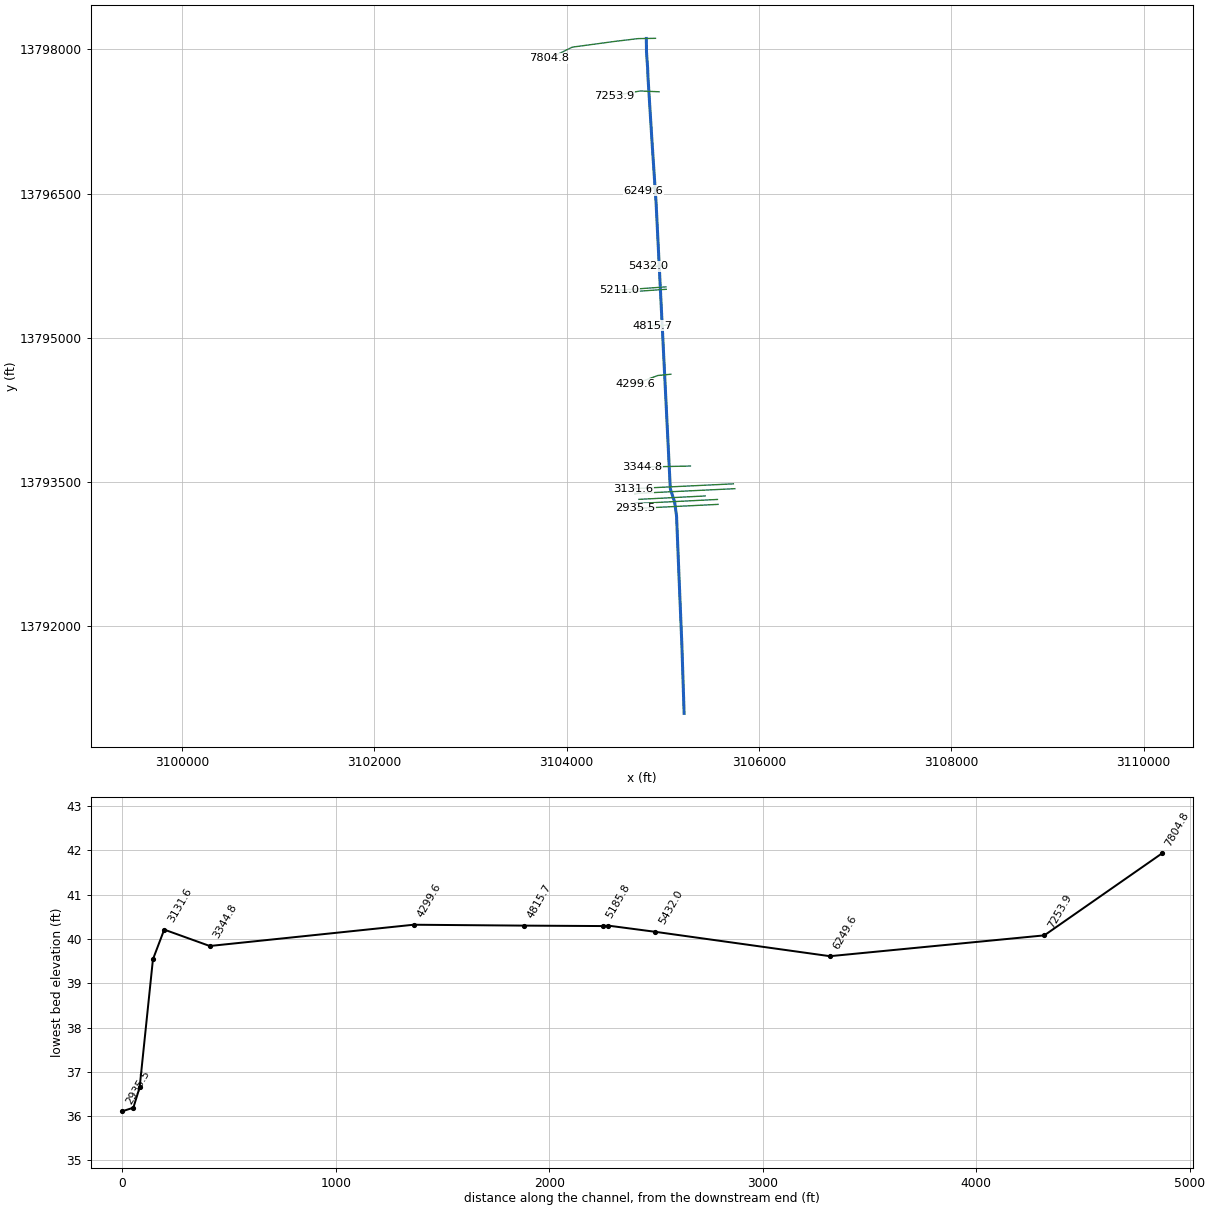
--- C161-00-00.PRJ (project) ---

Proj Title=C161-00-00
Current Plan=p02
Default Exp/Contr=0.3,0.1
English Units
Geom File=g01
Flow File=f01
Flow File=f02
Plan File=p01
Plan File=p02
Y Axis Title=Elevation
X Axis Title(PF)=Main Channel Distance
X Axis Title(XS)=Station
BEGIN DESCRIPTION:
Sims Bayou Watershed
Tributary 17.82 to Sims Bayou
HCFCD Unit C161-00-00
Flood Hazard Model
10, 2, 1, 0.2% Event
Filename C161-00-00.prj
Prepared by:  Watershed Concepts  Date:
Reviewed by:                      Date:
STATUS FINAL
END DESCRIPTION:
DSS Export Rating Curves= 0
DSS Export Rating Curve Sorted= 0
DSS Export Volume Flow Curves= 0
DXF OffsetX= 0
DXF OffsetY= 0
DXF ScaleX= 1
DXF ScaleY= 10

--- C161-00-00.p02 (plan) ---

Plan Title=Effective Floodway 2015
Program Version=4.10
Short Identifier=RiskMAP FW
Geom File=g01
Flow File=f02
Subcritical Flow
K Sum by GR= 0
Std Step Tol= 0.01
Critical Tol= 0.01
Num of Std Step Trials= 20
Max Error Tol= 0.3
Flow Tol Ratio= 0.001
Split Flow NTrial= 30
Split Flow Tol= 0.02
Split Flow Ratio= 0.02
Log Output Level= 0
Friction Slope Method= 1
Unsteady Friction Slope Method= 2
Unsteady Bridges Friction Slope Method= 1
Parabolic Critical Depth
Global Vel Dist= 0 , 0 , 0
Global Log Level= 0
CheckData=True
Encroach Param=-1 ,0,0, 2
Encroach River=C161-00-00
Encroach Reach=Reach - 1
Encroach Node=7804.8
       1  4952.1  5031.1
Encroach Node=7253.9
       1  4956.5  5035.1
Encroach Node=6249.6
       1  4961.5  5040.3
Encroach Node=5432.0
       1  4961.9  5036.9
Encroach Node=5211.0
       1    4956  5043.2
Encroach Node=5198.4
       1    4956  5043.2
Encroach Node=5185.8
       1    4956  5043.2
Encroach Node=4815.7
       1  4957.7  5042.5
Encroach Node=4299.6
       1  4957.7  5042.5
Encroach Node=3344.8
       1  4939.2  5042.5
Encroach Node=3131.6
       1  4957.1  5044.9
Encroach Node=3105.2
       1  4957.1  5044.9
Encroach Node=3078.8
       1  4957.1  5044.9
Encroach Node=3016.5
       1 4959.94 5056.64
Encroach Node=3006.0
       1 4959.94 5056.64
Encroach Node=2987.1
       1  4959.9  5056.6
Encroach Node=2961.3
       1  4959.9  5056.6
Encroach Node=2935.5
       1  4959.9  5056.6
Encroach Node=2744.0
       1  4960.6  5044.2
Encroach Node=1945.4
       1  4961.2  5037.7
Encroach Node=1188.7
       1  4956.6  5038.2
Encroach Reach=C161-00-00_0012
Encroach Node=7804.8
       1  4952.1  5031.1
Encroach Node=7253.9
       1  4956.5  5035.1
Encroach Node=6249.6
       1  4961.5  5040.3
Encroach Node=5432.0
       1  4961.9  5036.9
Encroach Node=5211.0
       1    4956  5043.2
Encroach Node=5198.4
       1    4956  5043.2
Encroach Node=5185.8
       1    4956  5043.2
Encroach Node=4815.7
       1  4957.7  5042.5
Encroach Node=4299.6
       1  4957.7  5042.5
Encroach Node=3344.8
       1  4939.2  5042.5
Encroach Node=3131.6
       1  4957.1  5044.9
Encroach Node=3105.2
       1  4957.1  5044.9
Encroach Node=3078.8
       1  4957.1  5044.9
Encroach Node=3016.5
       1 4959.94 5056.64
Encroach Node=3006.0
       1 4959.94 5056.64
Encroach Node=2987.1
       1  4959.9  5056.6
Encroach Node=2961.3
       1  4959.9  5056.6
Encroach Node=2935.5
       1  4959.9  5056.6
Encroach Node=2744.0
       1  4960.6  5044.2
Encroach Node=1945.4
       1  4961.2  5037.7
Encroach Node=1188.7
       1  4956.6  5038.2
BEGIN DESCRIPTION:
FEMA Effective Risk Map Study Floodway May 02, 2019
END DESCRIPTION:
Computation Interval=1HOUR
Output Interval=1HOUR
Run HTab= 0
Run UNet= 0
Run PostProcess= 0
Run WQNet= 0
UNET Theta= 1
UNET Theta Warmup= 1
UNET ZTol= 0.02
UNET ZSATol= 0.1
UNET MxIter= 20
UNET MaxInSteps= 20
UNET DtIC= 0
UNET DtMin= 0
UNET MaxCRTS= 20
UNET WFStab= 2
UNET SFStab= 1
UNET WFX= 1
UNET SFX= 1
UNET DSS MLevel= 4
UNET DZMax Abort= 100
UNET Convert EG Bridges=-1
UNET Use Existing IB Tables=-1
UNET Froude Reduction=False
UNET Froude Limit= 1
UNET Froude Power= 10
UNET Time Slicing=0,0, 5
UNET Junction Losses=0
Instantaneous Interval=1HOUR
Write IC File= 0
Write IC File at Sim End=0
Echo Input=False
Echo Parameters=False
Echo Output=False
Write Detailed= 0
WQ AD Non Conservative
WQ ULTIMATE=-1
WQ Max Comp Step=1HOUR
WQ Output Interval=15MIN
WQ Output Selected Increments= 0
WQ Output face flow=0
WQ Output face velocity=0
WQ Output face area=0
WQ Output face dispersion=0
WQ Output cell volume=0
WQ Output cell surface area=0
WQ Output cell continuity=0
WQ Output cumulative cell continuity=0
WQ Output face conc=0
WQ Output face dconc_dx=0
WQ Output face courant=0
WQ Output face peclet=0
WQ Output face adv mass=0
WQ Output face disp mass=0
WQ Output cell mass=0
WQ Output cell source sink temp=0
WQ Output cell source sink nsm=0
WQ Output MaxMinRange=-1
WQ Daily Max Min Mean=-1
WQ Daily Range=0
WQ Daily Time=0
WQ Create Restart=0
WQ Fixed Restart=0
WQ System Summary=0
WQ Use Fixed Temperature=0
Sorting and Armoring Iterations= 10
XS Update Threshold= 0.02
Hydraulics Update Threshold= 0.02
Energy Slope Method= 1
Volume Change Method= 0
XS Weighting Method= 0
Number of US Weighted Cross Sections= 1
Number of DS Weighted Cross Sections= 1
Upstream XS Weight=0.25
Main XS Weight=0.5
Downstream XS Weight=0.25
Number of DS XS's Weighted with US Boundary= 1
Upstream Boundary Weight= 1
Weight of XSs Associated with US Boundary= 0
Number of US XS's Weighted with DS Boundary= 1
Downstream Boundary Weight= 0.5
Weight of XSs Associated with DS Boundary= 0.5
Sediment Output Level= 4
Mass or Volume Output= 0
Output Increment Type= 1
Profile and TS Output Increment= 10
XS Output Flag= 0
XS Output Increment= 10
Disregard all LS=0
Disregard all Conn=0
Disregard all Breaches=0
Disregard all Pumps=0

--- C161-00-00.p01 (plan) ---

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Plan Title=Effective Multi-Profile 2015
Short Identifier=RiskMAP MP
Geom File=g01
Flow File=f01
Encroach Param=-1 ,0,0, 0
FEMA Effective Risk Map Study Multi-Profile May 02, 2019

--- C161-00-00.f02 (steady flow) ---

Flow Title=Effective Floodway 2015
Program Version=4.10
Number of Profiles= 2
Profile Names=1PCT_100yr,Floodway
River Rch & RM=C161-00-00,C161-00-00_0012 ,7804.8
    1019    1019
River Rch & RM=C161-00-00,C161-00-00_0012 ,5432
    1174    1174
River Rch & RM=C161-00-00,C161-00-00_0012 ,4299.6
    1327    1327
River Rch & RM=C161-00-00,C161-00-00_0012 ,3344.8
    1378    1378
River Rch & RM=C161-00-00,C161-00-00_0012 ,1188.7
    1429    1429
Boundary for River Rch & Prof#=C161-00-00,C161-00-00_0012 , 1
Up Type= 0
Dn Type= 3
Dn Slope=0.0023
Boundary for River Rch & Prof#=C161-00-00,C161-00-00_0012 , 2
Up Type= 0
Dn Type= 1
Dn Known WS=44.86
DSS Import GetInterval= 0
DSS Import GetPeak= 0
DSS Import FillOption= 0

--- C161-00-00.f01 (steady flow) ---

Flow Title=Effective Multi-Profile 2015
Program Version=4.10
Number of Profiles= 6
Profile Names=10PCT_10yr,4PCT_25yr,2PCT_50yr,1PCT_100yr,1PCT_Plus,0.2PCT_500yr
River Rch & RM=C161-00-00,C161-00-00_0012 ,7804.8
     548     705     854    1019    1222    1504
River Rch & RM=C161-00-00,C161-00-00_0012 ,5432
     632     814     986    1174    1409    1736
River Rch & RM=C161-00-00,C161-00-00_0012 ,4299.6
     713     919    1114    1327    1593    1962
River Rch & RM=C161-00-00,C161-00-00_0012 ,3344.8
     740     954    1156    1378    1654    2036
River Rch & RM=C161-00-00,C161-00-00_0012 ,1188.7
     768     990    1199    1429    1715    2110
Boundary for River Rch & Prof#=C161-00-00,C161-00-00_0012 , 1
Up Type= 0
Dn Type= 3
Dn Slope=0.0023
Boundary for River Rch & Prof#=C161-00-00,C161-00-00_0012 , 2
Up Type= 0
Dn Type= 3
Dn Slope=0.0023
Boundary for River Rch & Prof#=C161-00-00,C161-00-00_0012 , 3
Up Type= 0
Dn Type= 3
Dn Slope=0.0023
Boundary for River Rch & Prof#=C161-00-00,C161-00-00_0012 , 4
Up Type= 0
Dn Type= 3
Dn Slope=0.0023
DSS Import GetInterval= 0
DSS Import GetPeak= 0
DSS Import FillOption= 0

--- C161-00-00.g01 (geometry) ---

Geom Title=C161-00-00 2015
Program Version=4.10

River Reach=C161-00-00      ,C161-00-00_0012
Reach XY= 12
      3104828.51     13798113.95      3104829.96     13797971.54
      3104841.76     13797804.41      3104845.69      13797706.1
      3104890.92     13796984.49      3104930.24     13796392.66
      3105077.71     13793429.54      3105122.93     13793287.98
      3105142.59     13793144.44      3105166.19     13792562.44
      3105197.65     13791809.37      3105221.24      13791091.7

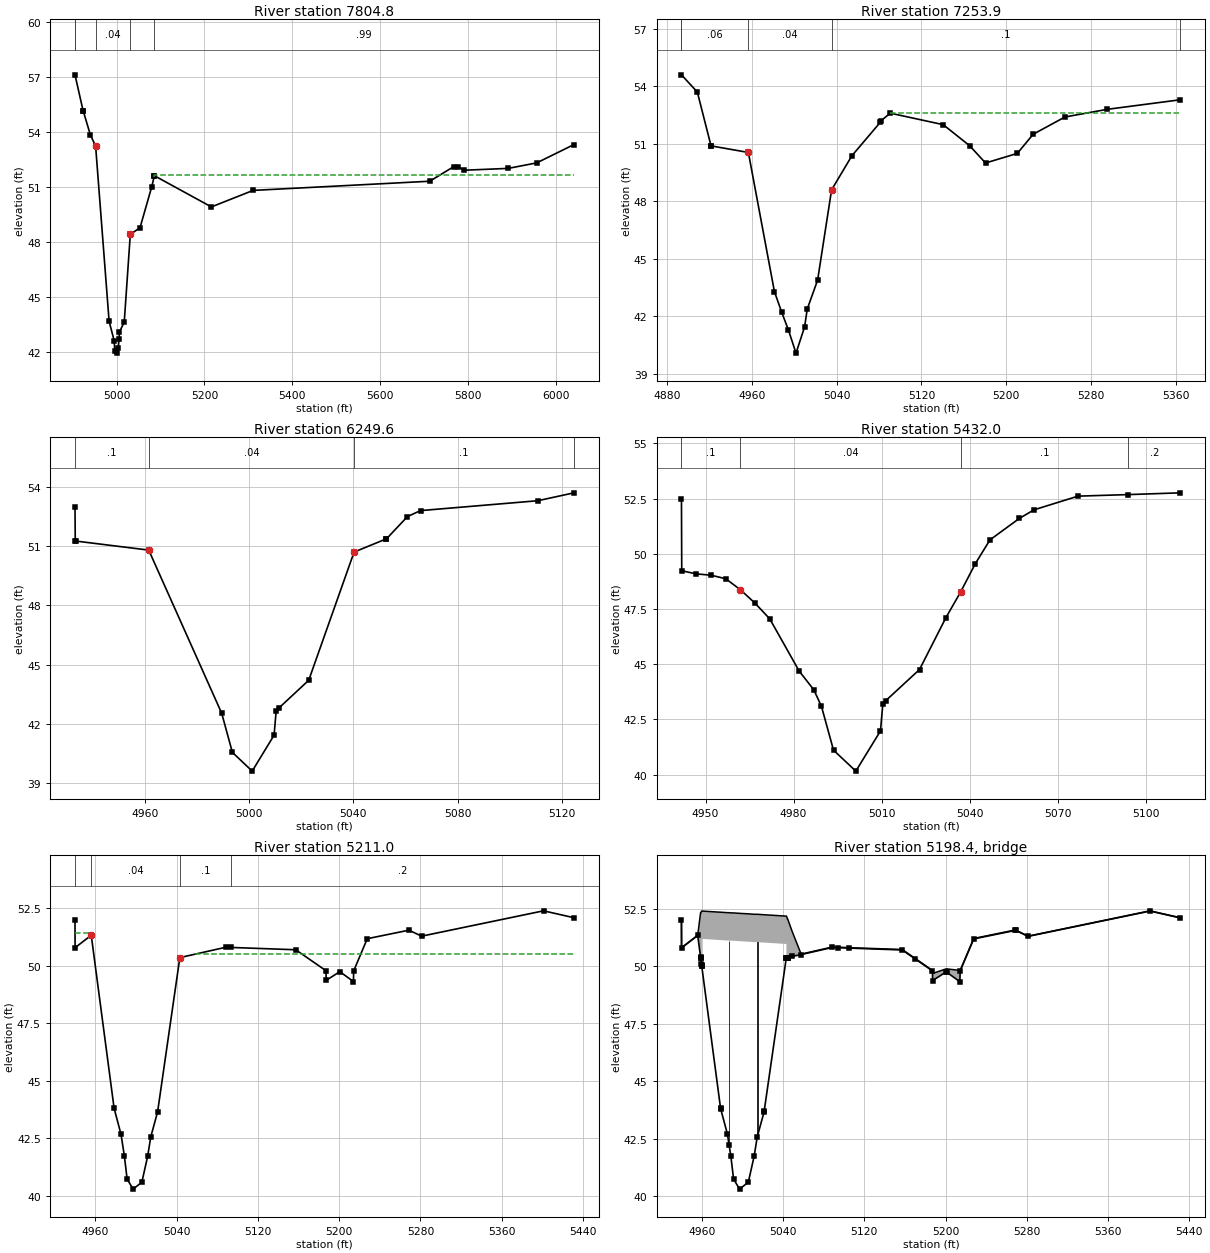
Type RM Length L Ch R = 1 ,7804.8  ,553.29,550.9,549.11
BEGIN DESCRIPTION:
Cross Section 7840.8
END DESCRIPTION:
XS GIS Cut Line= 5
      3104923.43     13798115.34      3104742.63     13798112.64
      3104497.07     13798082.96      3104057.22     13798023.59
      3103819.75     13797906.21
#Sta/Elev= 27
  4905.1    57.1  4923.5   55.15  4923.6   55.15    4940   53.84  4952.1   53.21
  4982.8   43.67  4994.4    42.6  4995.7   42.07  5000.4   41.93  5003.7   42.23
  5005.6   42.69  5006.3   43.08  5017.3   43.62  5031.1    48.4  5053.3   48.77
  5080.1   51.01  5085.9    51.6    5086    51.6  5215.9    49.9  5310.9    50.8
  5713.3    51.3  5768.3    52.1  5777.1    52.1  5792.1    51.9  5892.1      52
  5957.1    52.3    6042    53.3
#Mann= 5 , 1 , 0
  4905.1      .2       0  4905.1     .06       0  4952.1     .04       0
  5031.1      .1       0    5086     .99       0
#XS Ineff= 2 , 0
       0                    5085       0   51.66
Permanent Ineff=
       F       F
Bank Sta=4952.1,5031.1
XS Rating Curve= 0 ,0
Exp/Cntr=0.3,0.1

Type RM Length L Ch R = 1 ,7253.9  ,997.33,1004.3,1016.56
BEGIN DESCRIPTION:
Cross Section 7253.9
END DESCRIPTION:
XS GIS Cut Line= 3
       3104961.2     13797559.46      3104764.22     13797567.55
      3104494.37     13797518.98
#Sta/Elev= 25
  4893.3    54.6  4908.3    53.7  4921.2    50.9  4921.5   50.89  4956.5   50.55
  4981.1   43.29    4988   42.21  4994.3   41.29  5001.5   40.08  5009.6   41.45
  5012.1   42.38  5021.9   43.89  5035.1    48.6  5054.3   50.38  5081.2   52.13
  5081.3   52.18  5090.5    52.6  5140.5      52  5165.5    50.9  5180.5      50
  5210.5    50.5  5225.5    51.5  5255.5    52.4  5295.5    52.8  5364.6    53.3
#Mann= 5 , 1 , 0
  4893.3      .2       0  4893.3     .06       0  4956.5     .04       0
  5035.1      .1       0  5364.6      .2       0
#XS Ineff= 2 , 0
       0                  5090.7       0   52.63
Permanent Ineff=
       F       F
Bank Sta=4956.5,5035.1
XS Rating Curve= 0 ,0
Exp/Cntr=0.3,0.1

Type RM Length L Ch R = 1 ,6249.6  ,819.67,817.6,815.04
BEGIN DESCRIPTION:
Cross Section 6249.6
END DESCRIPTION:
XS GIS Cut Line= 3
      3104985.43     13796568.82      3104888.35     13796558.33
       3104799.3     13796528.64
#Sta/Elev= 18
  4933.2      53  4933.3   51.27  4933.4   51.26  4961.5    50.8  4989.5   42.54
  4993.6   40.56  5001.2   39.61  5009.6   41.43  5010.4   42.65  5011.4    42.8
  5022.9   44.21  5040.3    50.7  5052.5   51.36  5052.6   51.35  5060.8    52.5
  5065.8    52.8  5110.8    53.3  5124.7    53.7
#Mann= 4 , 1 , 0
  4933.2      .1       0  4961.5     .04       0  5040.3      .1       0
  5124.7      .2       0
Bank Sta=4961.5,5040.3
XS Rating Curve= 0 ,0
Exp/Cntr=0.3,0.1

Type RM Length L Ch R = 1 ,5432.0  ,215.27,221,222.44
BEGIN DESCRIPTION:
Cross Section 5432.0 - Interpolated
END DESCRIPTION:
XS GIS Cut Line= 2
      3105020.66     13795745.71      3104850.62     13795744.24
#Sta/Elev= 26
  4941.8    52.5  4941.9   49.23  4946.9   49.09  4951.9   49.03  4956.9   48.87
  4961.9   48.37  4966.9   47.76  4971.9   47.05  4981.9   44.69  4986.9   43.84
  4989.5   43.09  4993.6   41.11  5001.2   40.16  5009.6   41.98  5010.4    43.2
  5011.4   43.35  5022.9   44.76  5031.9   47.11  5036.9   48.27  5041.9   49.55
  5046.9   50.63  5056.9    51.6  5061.9   51.99  5076.9   52.61    5094   52.68
  5111.8   52.76
#Mann= 4 , 1 , 0
  4941.8      .1       0  4961.9     .04       0  5036.9      .1       0
    5094      .2       0
Bank Sta=4961.9,5036.9
XS Rating Curve= 0 ,0
Exp/Cntr=0.5,0.3

Type RM Length L Ch R = 1 ,5211.0  ,24.9,25.2,27.4
BEGIN DESCRIPTION:
Upstream Section of Bridge/Culvert/Weir
END DESCRIPTION:
XS GIS Cut Line= 2
      3105033.27     13795529.37      3104543.29     13795494.74
#Sta/Elev= 26
    4940   51.98  4940.1   50.78    4956   51.32  4978.5   43.81  4985.3   42.68
  4988.6   41.74  4991.3   40.74  4997.2    40.3  5005.8    40.6  5011.5   41.72
  5014.6   42.57  5021.3   43.65  5043.2   50.35  5088.6    50.8    5094   50.79
  5157.3   50.69  5187.1   49.78  5187.2   49.36  5200.7   49.74  5214.1   49.31
  5214.3   49.77  5227.7   51.17  5268.7   51.54  5281.2   51.28  5401.2   52.38
  5431.2   52.08
#Mann= 4 , 1 , 0
    4940      .1       0    4956     .04       0  5043.2      .1       0
    5094      .2       0
#XS Ineff= 2 , 0
       0    4955    51.4    5058       0    50.5
Permanent Ineff=
       F       F
Bank Sta=4956,5043.2
XS Rating Curve= 0 ,0
Exp/Cntr=0.5,0.3

Type RM Length L Ch R = 3 ,5198.4  ,,,
BEGIN DESCRIPTION:
Tidewater Drive
Structure ID: C16-3
END DESCRIPTION:
Bridge Culvert--1,0,-1,-1, 0
Deck Dist Width WeirC Skew NumUp NumDn MinLoCord MaxHiCord MaxSubmerge Is_Ogee
10,5.2,2.6,0, 48, 48, , , 0.95, 0, 1,1,,
    4940  4940.1    4956 4958.79  4958.9 4959.01  4959.7  4959.8 4959.91    4960
  4978.5  4978.6  4985.3  4986.9  4988.6  4991.3  4997.2  5005.8  5011.5  5014.6
  5021.3  5021.4  5043.2 5043.29  5043.4  5043.5 5044.39  5044.5 5044.61  5049.1
  5057.8  5088.6    5094  5105.2  5157.3  5169.8  5187.1  5187.2  5200.7  5200.9
  5214.1  5214.3  5227.7  5268.7  5269.1  5281.2  5401.2  5431.2
      52    50.8   51.34   52.31   52.31   52.31   52.38   52.39   52.39   52.39
   52.34   52.34   52.32   52.32   52.31   52.31   52.29   52.27   52.25   52.25
   52.23   52.23   52.17   52.17   52.17   52.16   52.04   52.04   52.04   51.49
   50.52   50.83   50.82    50.8   50.72   50.34   49.81   49.68   49.88   49.88
   49.81   49.81    51.2   51.57   51.56    51.3    52.4    52.1
   51.99   50.79   51.33    50.4   50.36   50.33    50.1   50.06   50.02   51.18
   51.13   51.13   51.11   51.11    51.1    51.1   51.08   51.06   51.04   51.04
   51.02   51.02   50.96   50.96   50.36   50.36   50.37   50.37   50.37   50.42
    50.5   50.81    50.8   50.78    50.7   50.32   49.79   49.37   49.75   49.74
   49.32   49.78   51.18   51.55   51.55   51.29   52.39   52.09
    4940  4940.1    4956 4958.79  4958.9 4959.01  4959.7  4959.8 4959.91    4960
  4978.5  4978.6  4985.3  4986.9  4988.6  4991.3  4997.2  5005.8  5011.5  5014.6
  5021.3  5021.4  5043.2 5043.29  5043.4  5043.5 5044.39  5044.5 5044.61  5049.1
  5057.8  5088.6    5094  5105.2  5157.3  5169.8  5187.1  5187.2  5200.7  5200.9
  5214.1  5214.3  5227.7  5268.7  5269.1  5281.2  5401.2  5431.2
      52    50.8   51.34   52.31   52.31   52.31   52.38   52.39   52.39   52.39
   52.34   52.34   52.32   52.32   52.31   52.31   52.29   52.27   52.25   52.25
   52.23   52.23   52.17   52.17   52.17   52.16   52.04   52.04   52.04   51.49
   50.52   50.83   50.82    50.8   50.72   50.34   49.81   49.68   49.88   49.88
   49.81   49.81    51.2   51.57   51.56    51.3    52.4    52.1
   51.97   50.77   51.31   50.38   50.34   50.31   50.08   50.04      50   51.16
   51.11   51.11   51.09   51.09   51.08   51.08   51.06   51.04   51.02   51.02
      51      51   50.94   50.94   50.34   50.34   50.35   50.35   50.35    50.4
   50.48   50.79   50.78   50.76   50.68    50.3   49.77   49.35   49.73   49.72
    49.3   49.76   51.16   51.53   51.53   51.27   52.37   52.07
Pier Skew, UpSta & Num, DnSta & Num=  ,4986.9, 2 ,4986.9, 2 , 0 , 0 , 0 ,,
      .6      .6
   41.14   52.11
      .6      .6
   41.12   52.09
Pier Skew, UpSta & Num, DnSta & Num=  ,5014.6, 2 ,5014.6, 2 , 0 , 0 , 0 ,,
      .6      .6
    41.5   52.04
      .6      .6
   41.48   52.02
Abutment Skew #Up #Dn= , 2 , 2
  4959.8  4978.6
   51.18    43.8
  4959.8  4978.6
   51.16   43.78
Abutment Skew #Up #Dn= , 2 , 2
  5021.4 5043.49
   43.69   50.96
  5021.4 5043.49
   43.67   50.94
BR Coef= 1 , 1 , 0 ,1.25, 0 ,,,0.8,0,2,0,
WSPro=,,,, 1 ,,,, 0 ,,,, 0 ,,,,-1 ,-1 ,-1 , 0 , 0 , 0 , 0 , 0
BR U #Sta/Elev= 48
    4940   51.99  4940.1   50.79    4956   51.33 4958.79    50.4  4958.9   50.36
 4959.01   50.33  4959.7    50.1  4959.8   50.06 4959.91   50.02    4960   49.99
  4978.5   43.82  4978.6    43.8  4985.3   42.69  4986.9   42.22  4988.6   41.75
  4991.3   40.75  4997.2   40.31  5005.8   40.61  5011.5   41.73  5014.6   42.58
  5021.3   43.66  5021.4   43.69  5043.2   50.36 5043.29   50.36  5043.4   50.36
  5043.5   50.36 5044.39   50.37  5044.5   50.37 5044.61   50.37  5049.1   50.42
  5057.8    50.5  5088.6   50.81    5094    50.8  5105.2   50.78  5157.3    50.7
  5169.8   50.32  5187.1   49.79  5187.2   49.37  5200.7   49.75  5200.9   49.74
  5214.1   49.32  5214.3   49.78  5227.7   51.18  5268.7   51.55  5269.1   51.55
  5281.2   51.29  5401.2   52.39  5431.2   52.09
BR U #Mann= 4
    4940      .1    4956     .04  5043.2      .1    5094      .2
BR U Banks=4956,5043.2
BR D #Sta/Elev= 48
    4940   51.97  4940.1   50.77    4956   51.31 4958.79   50.38  4958.9   50.34
 4959.01   50.31  4959.7   50.08  4959.8   50.04 4959.91      50    4960   49.97
  4978.5    43.8  4978.6   43.78  4985.3   42.67  4986.9    42.2  4988.6   41.73
  4991.3   40.73  4997.2   40.29  5005.8   40.59  5011.5   41.71  5014.6   42.56
  5021.3   43.64  5021.4   43.67  5043.2   50.34 5043.29   50.34  5043.4   50.34
  5043.5   50.34 5044.39   50.35  5044.5   50.35 5044.61   50.35  5049.1    50.4
  5057.8   50.48  5088.6   50.79    5094   50.78  5105.2   50.76  5157.3   50.68
  5169.8    50.3  5187.1   49.77  5187.2   49.35  5200.7   49.73  5200.9   49.72
  5214.1    49.3  5214.3   49.76  5227.7   51.16  5268.7   51.53  5269.1   51.53
  5281.2   51.27  5401.2   52.37  5431.2   52.07
BR D #Mann= 4
    4940      .1    4956     .04  5043.2      .1    5094      .2
BR D Banks=4956,5043.2
BC Design=,, 0 ,, 0 ,,,,,,
BC HTab HWMax=52.38
BC Use User HTab Curves=0
BC User HTab FreeFlow(D)= 0

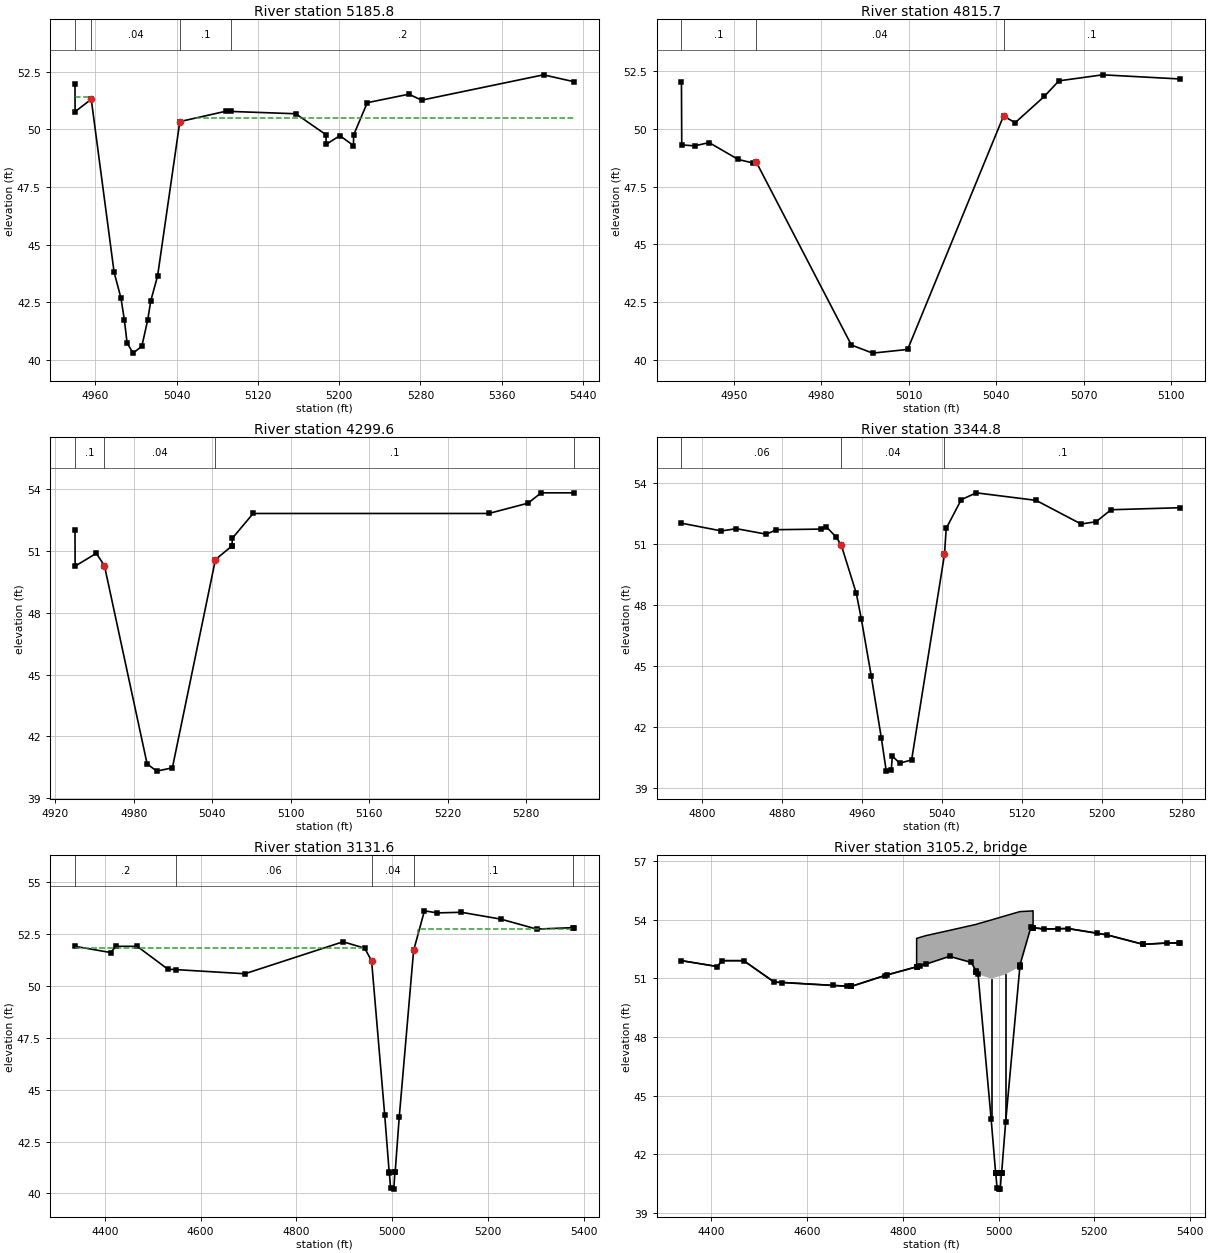
Type RM Length L Ch R = 1 ,5185.8  ,368.2,370.1,364.7
BEGIN DESCRIPTION:
Downstream Section of Bridge/Culvert/Weir
END DESCRIPTION:
XS GIS Cut Line= 2
      3105034.52      13795504.2      3104544.54     13795469.58
#Sta/Elev= 26
    4940   51.97  4940.1   50.77    4956   51.31  4978.5    43.8  4985.3   42.67
  4988.6   41.73  4991.3   40.73  4997.2   40.29  5005.8   40.59  5011.5   41.71
  5014.6   42.56  5021.3   43.64  5043.2   50.34  5088.6   50.79    5094   50.78
  5157.3   50.68  5187.1   49.77  5187.2   49.35  5200.7   49.73  5214.1    49.3
  5214.3   49.76  5227.7   51.16  5268.7   51.53  5281.2   51.27  5401.2   52.37
  5431.2   52.07
#Mann= 4 , 1 , 0
    4940      .1       0    4956     .04       0  5043.2      .1       0
    5094      .2       0
#XS Ineff= 2 , 0
       0    4955    51.4    5058       0    50.5
Permanent Ineff=
       F       F
Bank Sta=4956,5043.2
XS Rating Curve= 0 ,0
Exp/Cntr=0.5,0.3

Type RM Length L Ch R = 1 ,4815.7  ,512.2,516.1,517.7
BEGIN DESCRIPTION:
Cross Section 4815.7 - Interpolated
END DESCRIPTION:
XS GIS Cut Line= 2
      3105060.99     13795133.44      3104890.04     13795123.94
#Sta/Elev= 16
    4932      52  4932.1    49.3  4936.5   49.26  4941.5    49.4  4951.5   48.67
  4956.5   48.52  4957.7   48.55  4990.3   40.65  4997.6    40.3  5009.6   40.46
  5042.5   50.55  5046.5   50.26  5056.5    51.4  5061.5   52.07  5076.5   52.33
  5103.2   52.15
#Mann= 3 , 1 , 0
    4932      .1       0  4957.7     .04       0  5042.5      .1       0
Bank Sta=4957.7,5042.5
XS Rating Curve= 0 ,0
Exp/Cntr=0.3,0.1

Type RM Length L Ch R = 1 ,4299.6  ,957.87,954.8,950.4
BEGIN DESCRIPTION:
Cross Section 4299.6
END DESCRIPTION:
XS GIS Cut Line= 3
      3105083.26     13794620.37      3104947.71     13794607.34
      3104718.34     13794520.99
#Sta/Elev= 16
  4935.2      52  4935.3   50.25  4951.5   50.87  4957.7   50.27  4990.3   40.67
  4997.6   40.32  5009.6   40.48  5042.5   50.57    5055   51.22  5055.1   51.21
  5055.4    51.6  5071.3    52.8  5251.3    52.8  5281.3    53.3  5291.3    53.8
  5316.4    53.8
#Mann= 4 , 1 , 0
  4935.2      .1       0  4957.7     .04       0  5042.5      .1       0
  5316.4      .2       0
Bank Sta=4957.7,5042.5
XS Rating Curve= 0 ,0
Exp/Cntr=0.3,0.1

Type RM Length L Ch R = 1 ,3344.8  ,212.6,213.2,216.6
BEGIN DESCRIPTION:
Cross Section 3344.8 - Interpolateed
END DESCRIPTION:
XS GIS Cut Line= 2
      3105286.93     13793665.19      3104787.54     13793654.67
#Sta/Elev= 27
  4779.2   52.01  4819.2   51.63  4834.2   51.74  4864.2   51.47  4874.2   51.69
  4919.2   51.72  4924.2   51.83  4934.2   51.32  4939.2   50.93  4954.2   48.57
  4959.2   47.32  4969.2   44.51  4979.2   41.49  4984.2   39.84  4989.2    39.9
  4990.3   40.58  4997.6   40.23  5009.6   40.39  5042.5   50.48  5044.2   51.75
  5059.2   53.16  5074.2    53.5  5134.2   53.13  5179.2   51.97  5194.2   52.08
  5209.2   52.67  5278.7   52.77
#Mann= 3 , 1 , 0
  4779.2     .06       0  4939.2     .04       0  5042.5      .1       0
Bank Sta=4939.2,5042.5
XS Rating Curve= 0 ,0
Exp/Cntr=0.5,0.3

Type RM Length L Ch R = 1 ,3131.6  ,53.8,52.8,52.7
BEGIN DESCRIPTION:
Upstream Section of Bridge/Culvert/Weir
END DESCRIPTION:
XS GIS Cut Line= 2
       3105733.6     13793479.91       3104692.2     13793429.93
#Sta/Elev= 26
  4337.4    51.9  4412.4    51.6  4422.4    51.9  4467.4    51.9  4531.4    50.8
    4548   50.78  4692.4   50.58  4897.5   52.12  4942.7   51.81  4957.1    51.2
  4984.5   43.78  4993.9   41.01  4994.1   41.02  4996.8   40.26  5003.5   40.21
  5005.8   41.02  5006.3   41.02  5014.8   43.66  5044.9    51.7  5067.5   53.61
  5094.5   53.51  5144.6   53.54  5227.3   53.21  5302.2   52.73  5377.9    52.8
    5380    52.8
#Mann= 5 , 1 , 0
  4337.4      .2       0    4548     .06       0  4957.1     .04       0
  5044.9      .1       0  5377.9      .2       0
#XS Ineff= 2 , 0
       0    4940   51.84    5054       0   52.75
Permanent Ineff=
       F       F
Bank Sta=4957.1,5044.9
XS Rating Curve= 0 ,0
Exp/Cntr=0.5,0.3

Type RM Length L Ch R = 3 ,3105.2  ,,,
BEGIN DESCRIPTION:
Westbound Orem Drive
Structure ID: C16-2
END DESCRIPTION:
Bridge Culvert--1,0,-1,-1, 0
Deck Dist Width WeirC Skew NumUp NumDn MinLoCord MaxHiCord MaxSubmerge Is_Ogee
10,32.8,2.6,0, 53, 53, , , 0.95, 0, 1,1,,
  4337.4  4412.4  4422.4  4467.4  4531.4    4548    4653    4683  4691.6  4692.3
  4692.4    4763  4765.9 4828.69  4828.8 4828.91  4836.8    4848  4897.5  4942.7
  4953.6 4953.71  4953.8  4957.1  4984.5  4993.8  4993.9  4994.1  4996.8  5000.2
  5003.5  5005.8  5006.2  5006.3  5014.8 5044.49  5044.6  5044.7  5044.9  5067.5
 5071.89    5072 5072.11  5094.5  5124.2  5144.6  5205.8  5227.3  5302.2  5302.5
  5352.7  5377.9    5380
    51.9    51.6    51.9    51.9    50.8   50.79   50.64    50.6   50.59   50.59
   50.59   51.15   51.17   51.59   53.04   53.04    53.1   53.18   53.45    53.7
   53.76   53.76   53.76   53.79   53.98   54.05   54.05   54.05   54.07   54.09
   54.12   54.13   54.14   54.14    54.2   54.41   54.41   54.41   54.41   54.44
   54.45   54.45    53.6   53.52   53.54   53.55   53.31   53.22   52.74   52.74
   52.81   52.81    52.8
    51.9    51.6    51.9    51.9    50.8   50.78   50.63   50.59   50.58   50.58
   50.58   51.14   51.16   51.58   51.58   51.58   51.63   51.72   52.12   51.81
   51.35   51.34   51.34    51.2   50.98   51.05   51.05   51.05   51.07   51.09
   51.12   51.13   51.14   51.14    51.2   51.59   51.62   51.65    51.7   53.61
   53.59   53.59   53.59   53.51   53.53   53.54    53.3   53.21   52.73   52.73
    52.8    52.8    52.8
  4337.4  4412.4  4422.4  4467.4  4531.4    4548    4653    4683  4691.6  4692.3
  4692.4    4763  4765.9 4828.69  4828.8 4828.91  4836.8    4848  4897.5  4942.7
  4953.6 4953.71  4953.8  4957.1  4984.5  4993.8  4993.9  4994.1  4996.8  5000.2
  5003.5  5005.8  5006.2  5006.3  5014.8 5044.49  5044.6  5044.7  5044.9  5067.5
 5071.89    5072 5072.11  5094.5  5124.2  5144.6  5205.8  5227.3  5302.2  5302.5
  5352.7  5377.9    5380
    51.9    51.6    51.9    51.9    50.8   50.79   50.64    50.6   50.59   50.59
   50.59   51.15   51.17   51.59   53.04   53.04    53.1   53.18   53.45    53.7
   53.76   53.76   53.76   53.79   53.98   54.05   54.05   54.05   54.07   54.09
   54.12   54.13   54.14   54.14    54.2   54.41   54.41   54.41   54.41   54.44
   54.45   54.45    53.6   53.52   53.54   53.55   53.31   53.22   52.74   52.74
   52.81   52.81    52.8
   51.69   51.39   51.69   51.69   50.59   50.57   50.42   50.38   50.37   50.37
   50.37   50.93   50.95   51.37   51.37   51.37   51.42   51.51   51.91    51.6
   51.14   51.13   51.13   50.99   50.77   50.84   50.84   50.84   50.86   50.88
   50.91   50.92   50.93   50.93   50.99   51.38   51.41   51.44   51.49    53.4
   53.38   53.38   53.38    53.3   53.32   53.33   53.09      53   52.52   52.52
   52.59   52.59   52.59
Pier Skew, UpSta & Num, DnSta & Num=  ,4984.5, 2 ,4984.5, 2 , 0 , 0 , 0 ,,
     1.4     1.4
   42.57   51.99
     1.4     1.4
   42.36   51.78
Pier Skew, UpSta & Num, DnSta & Num=  ,5014.8, 2 ,5014.8, 2 , 0 , 0 , 0 ,,
     1.4     1.4
   42.44   52.21
     1.4     1.4
   42.23      52
Abutment Skew #Up #Dn= , 2 , 2
  4953.6  4993.9
   51.34   41.01
  4953.6  4993.9
   51.13    40.8
Abutment Skew #Up #Dn= , 2 , 2
  5006.3 5044.69
   41.02   51.59
  5006.3 5044.69
   40.81   51.38
BR Coef= 1 , 1 , 0 ,1.25, 0 ,,,0.8,0,2,0,
WSPro=,,,, 1 ,,,, 0 ,,,, 0 ,,,,-1 ,-1 ,-1 , 0 , 0 , 0 , 0 , 0
BR U #Sta/Elev= 53
  4337.4    51.9  4412.4    51.6  4422.4    51.9  4467.4    51.9  4531.4    50.8
    4548   50.78    4653   50.63    4683   50.59  4691.6   50.58  4692.3   50.58
  4692.4   50.58    4763   51.14  4765.9   51.16 4828.69   51.58  4828.8   51.58
 4828.91   51.58  4836.8   51.63    4848   51.72  4897.5   52.12  4942.7   51.81
  4953.6   51.35 4953.71   51.34  4953.8   51.34  4957.1    51.2  4984.5   43.78
  4993.8   41.04  4993.9   41.01  4994.1   41.02  4996.8   40.26  5000.2   40.22
  5003.5   40.21  5005.8   41.02  5006.2   41.02  5006.3   41.02  5014.8   43.66
 5044.49   51.59  5044.6   51.62  5044.7   51.65  5044.9    51.7  5067.5   53.61
 5071.89   53.59    5072   53.59 5072.11   53.59  5094.5   53.51  5124.2   53.53
  5144.6   53.54  5205.8    53.3  5227.3   53.21  5302.2   52.73  5302.5   52.73
  5352.7    52.8  5377.9    52.8    5380    52.8
BR U #Mann= 5
  4337.4      .2    4548     .06  4957.1     .04  5044.9      .1  5377.9      .2
BR U Banks=4957.1,5044.9
BR D #Sta/Elev= 53
  4337.4   51.69  4412.4   51.39  4422.4   51.69  4467.4   51.69  4531.4   50.59
    4548   50.57    4653   50.42    4683   50.38  4691.6   50.37  4692.3   50.37
  4692.4   50.37    4763   50.93  4765.9   50.95 4828.69   51.37  4828.8   51.37
 4828.91   51.37  4836.8   51.42    4848   51.51  4897.5   51.91  4942.7    51.6
  4953.6   51.14 4953.71   51.13  4953.8   51.13  4957.1   50.99  4984.5   43.57
  4993.8   40.83  4993.9    40.8  4994.1   40.81  4996.8   40.05  5000.2   40.01
  5003.5      40  5005.8   40.81  5006.2   40.81  5006.3   40.81  5014.8   43.45
 5044.49   51.38  5044.6   51.41  5044.7   51.44  5044.9   51.49  5067.5    53.4
 5071.89   53.38    5072   53.38 5072.11   53.38  5094.5    53.3  5124.2   53.32
  5144.6   53.33  5205.8   53.09  5227.3      53  5302.2   52.52  5302.5   52.52
  5352.7   52.59  5377.9   52.59    5380   52.59
BR D #Mann= 5
  4337.4      .2    4548     .06  4957.1     .04  5044.9      .1  5377.9      .2
BR D Banks=4957.1,5044.9
BC Design=,, 0 ,, 0 ,,,,,,
BC HTab HWMax=53.61
BC Use User HTab Curves=0
BC User HTab FreeFlow(D)= 0

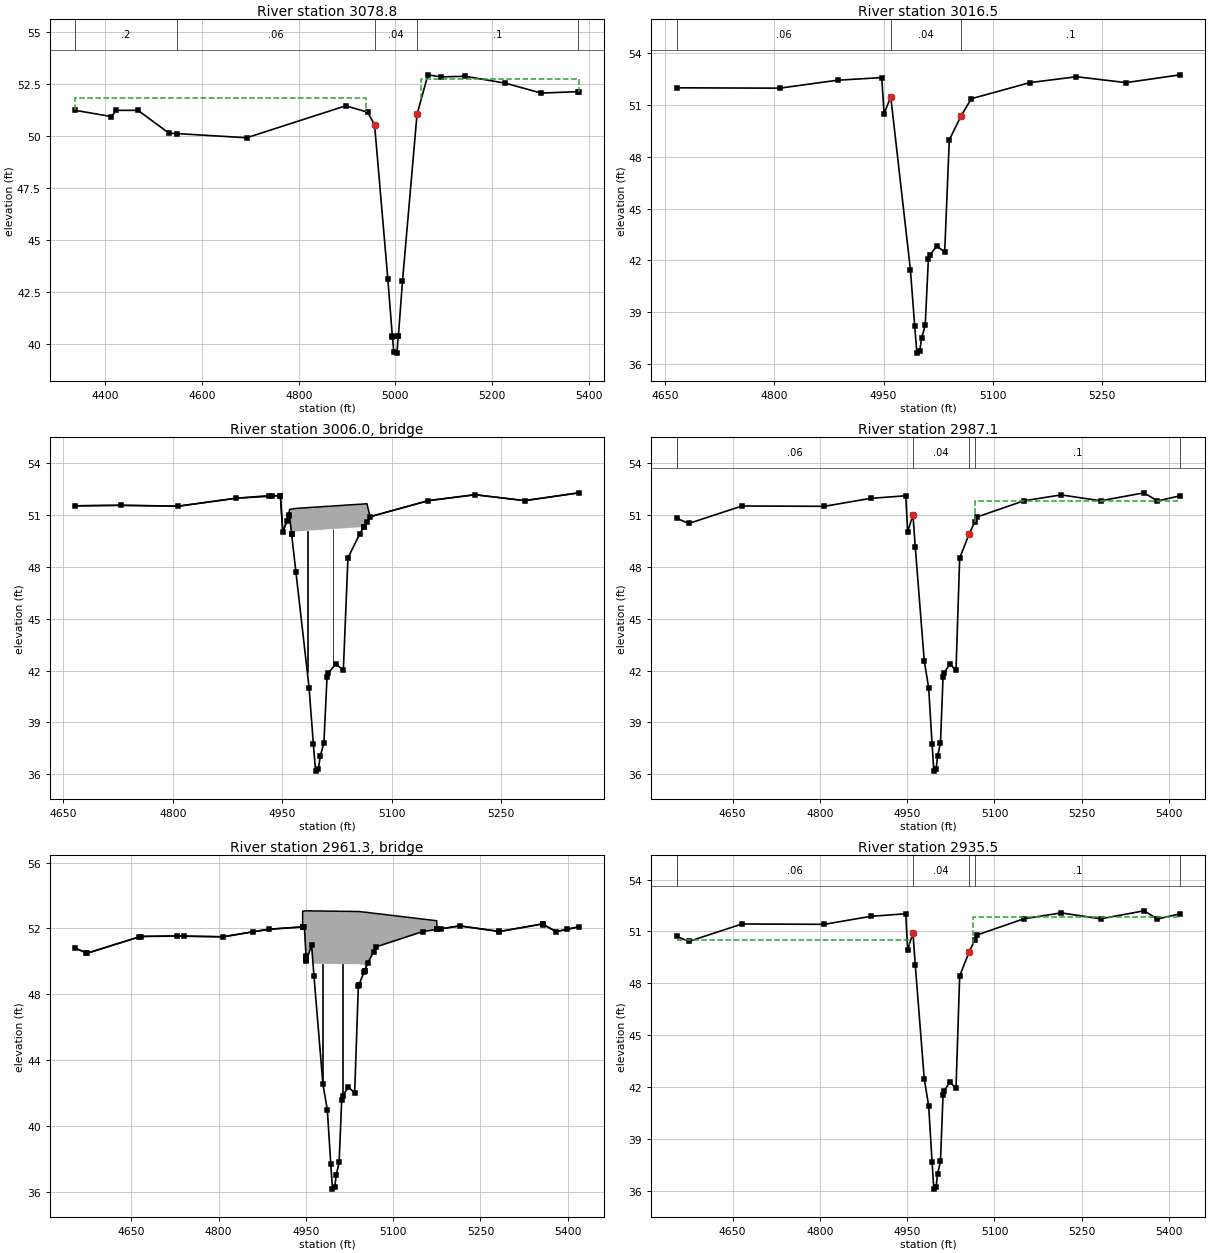
Type RM Length L Ch R = 1 ,3078.8  ,61.1,62.3,64
BEGIN DESCRIPTION:
Downstream Section of Bridge/Culvert/Weir
END DESCRIPTION:
XS GIS Cut Line= 2
      3105749.67     13793429.62      3104708.27     13793379.63
#Sta/Elev= 26
  4337.4   51.23  4412.4   50.93  4422.4   51.23  4467.4   51.23  4531.4   50.13
    4548   50.11  4692.4   49.91  4897.5   51.45  4942.7   51.14  4957.1   50.53
  4984.5   43.11  4993.9   40.34  4994.1   40.35  4996.8   39.59  5003.5   39.54
  5005.8   40.35  5006.3   40.35  5014.8   42.99  5044.9   51.03  5067.5   52.94
  5094.5   52.84  5144.6   52.87  5227.3   52.54  5302.2   52.06  5377.9   52.13
    5380   52.13
#Mann= 5 , 1 , 0
  4337.4      .2       0    4548     .06       0  4957.1     .04       0
  5044.9      .1       0  5377.9      .2       0
#XS Ineff= 2 , 0
       0    4940   51.84    5054       0   52.75
Permanent Ineff=
       F       F
Bank Sta=4957.1,5044.9
XS Rating Curve= 0 ,0
Exp/Cntr=0.5,0.3

Type RM Length L Ch R = 1 ,3016.5  ,30.6,29.4,29.1
BEGIN DESCRIPTION:
Upstream Section of Bridge/Culvert/Weir
END DESCRIPTION:
XS GIS Cut Line= 2
      3105440.76     13793353.91      3104750.76      13793318.5
#Sta/Elev= 23
 4666.14   51.97 4807.64   51.95 4887.14   52.41 4947.54   52.56 4950.84   50.48
 4959.94   51.45 4986.94   41.46 4992.84   38.19 4995.84   36.65 4999.74   36.79
 5002.24   37.51 5007.24   38.27 5011.54   42.07 5013.24   42.31 5023.24   42.83
 5033.94   42.49 5040.24   48.96 5056.64   50.37 5070.54   51.34 5150.74   52.27
 5214.64   52.61 5282.74   52.27 5357.04   52.72
#Mann= 3 , 1 , 0
 4666.14     .06       0 4959.94     .04       0 5056.64      .1       0
#XS Ineff= 2 , 0
       0 4949.94   50.03 5066.64       0   50.88
Permanent Ineff=
       F       F
Bank Sta=4959.94,5056.64
XS Rating Curve= 0 ,0
Exp/Cntr=0.5,0.3

Type RM Length L Ch R = 3 ,3006.0  ,,,
BEGIN DESCRIPTION:
Pipe Line
END DESCRIPTION:
Bridge Culvert--1,0,-1,-1, 0
Deck Dist Width WeirC Skew NumUp NumDn MinLoCord MaxHiCord MaxSubmerge Is_Ogee
10,1,2.6,0, 35, 35, , , 0.95, 0, 1,1,,
 4666.14 4728.44 4807.64 4887.14  4931.6  4936.6  4946.6 4947.54 4950.84  4956.7
 4959.94 4960.04 4962.85 4962.94 4968.94 4986.94 4992.84 4995.84 4999.74 5002.24
 5007.24 5011.54 5013.24 5023.24 5033.94 5040.24 5056.64 5062.03 5062.14 5066.34
 5070.54 5150.74 5214.64 5282.74 5357.04
   51.51   51.54   51.49   51.95    52.1   52.08   52.11   52.11   50.03   50.65
   51.22    51.3   51.32   51.32   51.36   51.41   51.43   51.43   51.45   51.45
   51.47   51.48   51.48   51.51   51.54   51.56    51.6   51.62   51.62   51.63
   50.88   51.81   52.15   51.81   52.26
   51.51   51.54   51.49   51.95   52.06   52.07    52.1    52.1   50.02   50.64
   50.99   50.95   49.91   49.99   50.03   50.08    50.1    50.1   50.12   50.12
   50.14   50.15   50.15   50.18   50.21   50.23   50.27   50.29   50.29   50.59
   50.88   51.81   52.15   51.81   52.26
 4666.14 4728.44 4807.64 4887.14  4931.6  4936.6  4946.6 4947.54 4950.84  4956.7
 4959.94 4960.04 4962.85 4962.94 4968.94 4986.94 4992.84 4995.84 4999.74 5002.24
 5007.24 5011.54 5013.24 5023.24 5033.94 5040.24 5056.64 5062.03 5062.14 5066.34
 5070.54 5150.74 5214.64 5282.74 5357.04
   51.51   51.54   51.49   51.95    52.1   52.08   52.11   52.11   50.03   50.65
   51.22    51.3   51.32   51.32   51.36   51.41   51.43   51.43   51.45   51.45
   51.47   51.48   51.48   51.51   51.54   51.56    51.6   51.62   51.62   51.63
   50.88   51.81   52.15   51.81   52.26
   51.51   51.54   51.49   51.95   52.06   52.07    52.1    52.1   50.02   50.64
   50.99   50.95   49.91   49.99   50.03   50.08    50.1    50.1   50.12   50.12
   50.14   50.15   50.15   50.18   50.21   50.23   50.27   50.29   50.29   50.59
   50.88   51.81   52.15   51.81   52.26
Pier Skew, UpSta & Num, DnSta & Num=  ,4984.4, 2 ,4984.4, 2 , 0 , 0 , 0 ,,
       1       1
   40.74   51.07
       1       1
   40.74   51.07
Pier Skew, UpSta & Num, DnSta & Num=  ,5019.9, 2 ,5019.9, 2 , 0 , 0 , 0 ,,
       1       1
   41.17   51.17
       1       1
   41.17   51.17
BR Coef= 1 , 1 , 0 ,1.25, 0 ,,,0.8,0,2,0,
WSPro=,,,, 1 ,,,, 0 ,,,, 0 ,,,,-1 ,-1 ,-1 , 0 , 0 , 0 , 0 , 0
BR U #Sta/Elev= 35
 4666.14   51.51 4728.44   51.54 4807.64   51.49 4887.14   51.95  4931.6   52.06
  4936.6   52.07  4946.6    52.1 4947.54    52.1 4950.84   50.02  4956.7   50.64
 4959.94   50.99 4960.04   50.95 4962.85   49.91 4962.94   49.88 4968.94   47.66
 4986.94      41 4992.84   37.73 4995.84   36.19 4999.74   36.33 5002.24   37.05
 5007.24   37.81 5011.54   41.61 5013.24   41.85 5023.24   42.37 5033.94   42.03
 5040.24    48.5 5056.64   49.91 5062.03   50.29 5062.14   50.29 5066.34   50.59
 5070.54   50.88 5150.74   51.81 5214.64   52.15 5282.74   51.81 5357.04   52.26
BR U #Mann= 3
 4666.14     .06 4959.94     .04 5056.64      .1
BR U Banks=4959.94,5056.64
BR D #Sta/Elev= 35
 4666.14   51.51 4728.44   51.54 4807.64   51.49 4887.14   51.95  4931.6   52.06
  4936.6   52.07  4946.6    52.1 4947.54    52.1 4950.84   50.02  4956.7   50.64
 4959.94   50.99 4960.04   50.95 4962.85   49.91 4962.94   49.88 4968.94   47.66
 4986.94      41 4992.84   37.73 4995.84   36.19 4999.74   36.33 5002.24   37.05
 5007.24   37.81 5011.54   41.61 5013.24   41.85 5023.24   42.37 5033.94   42.03
 5040.24    48.5 5056.64   49.91 5062.03   50.29 5062.14   50.29 5066.34   50.59
 5070.54   50.88 5150.74   51.81 5214.64   52.15 5282.74   51.81 5357.04   52.26
BR D #Mann= 3
 4666.14     .06 4959.94     .04 5056.64      .1
BR D Banks=4959.94,5056.64
BC Design=,, 0 ,, 0 ,,,,,,
BC HTab HWMax=52.72
BC Use User HTab Curves=0
BC User HTab FreeFlow(D)= 0

Type RM Length L Ch R = 1 ,2987.1  ,51.8,51.6,48.3
BEGIN DESCRIPTION:
Upstream Section of Bridge/Culvert/Weir
END DESCRIPTION:
XS GIS Cut Line= 2
      3105567.77     13793317.47      3104703.13     13793274.65
#Sta/Elev= 30
  4553.6    50.8  4574.5    50.5  4666.1   51.51  4807.6   51.49  4887.1   51.95
  4947.5    52.1  4950.8   50.02  4959.9   50.99  4963.9   49.13  4979.3   42.57
  4986.9      41  4992.8   37.73  4995.8   36.19  4999.7   36.33  5002.2   37.05
  5007.2   37.81  5011.6   41.61  5013.2   41.85  5023.2   42.37  5033.9   42.03
  5040.2    48.5  5056.6   49.91  5066.4   50.59  5070.5   50.88  5150.7   51.81
  5214.6   52.15  5282.7   51.81  5356.9   52.27  5380.2    51.8  5419.3    52.1
#Mann= 6 , 1 , 0
  4553.6      .2       0  4553.6     .06       0  4959.9     .04       0
  5056.6     .06       0  5066.4      .1       0  5419.3      .2       0
#XS Ineff= 2 , 0
       0  4949.9   50.51  5066.6       0   51.81
Permanent Ineff=
       F       F
Bank Sta=4959.9,5056.6
XS Rating Curve= 0 ,0
Exp/Cntr=0.5,0.3

Type RM Length L Ch R = 3 ,2961.3  ,,,
BEGIN DESCRIPTION:
Eastbound Orem Drive
Structure ID: C16-1
END DESCRIPTION:
Bridge Culvert--1,0,-1,-1, 0
Deck Dist Width WeirC Skew NumUp NumDn MinLoCord MaxHiCord MaxSubmerge Is_Ogee
10,31.6,2.6,0, 55, 55, , , 0.95, 0, 1,1,,
  4553.6  4571.5  4574.5  4663.2  4666.1  4728.4  4741.3  4807.6  4858.6  4887.1
 4944.39  4944.5 4944.61  4947.5  4950.3 4950.41  4950.5  4950.7  4950.8  4959.9
  4963.9  4979.3  4986.9  4992.8  4995.8  4999.7  5002.2  5007.2  5011.6  5013.2
  5023.2  5033.9  5040.2  5041.1  5041.2  5050.2 5051.09  5051.2  5056.6  5066.4
  5070.5  5150.7 5174.99  5175.1 5175.21    5183  5214.6  5281.3  5282.7  5356.9
    5357  5358.1  5380.2  5398.2  5419.3
    50.8   50.55   50.51   51.49   51.52   51.55   51.54    51.5    51.8   51.96
    52.1   53.05   53.05   53.06   53.07   53.07   53.07   53.07   53.07   53.07
   53.06   53.06   53.05   53.05   53.05   53.05   53.05   53.04   53.04   53.04
   53.04   53.03   53.03   53.03   53.03   52.99   52.99   52.99   52.97   52.92
   52.91   52.57   52.47   52.47   51.95   51.99   52.16   51.83   51.82   52.28
   52.27   52.25   51.81   51.95    52.1
    50.8   50.54    50.5   51.48   51.51   51.54   51.53   51.49   51.79   51.95
   52.09   52.09   52.09    52.1   50.34   50.27   50.21   50.08   50.02   50.99
   49.86   49.86   49.85   49.85   49.85   49.85   49.85   49.84   49.84   49.84
   49.84   49.83   49.83   49.83   49.83   49.79   49.79   49.45   49.91   50.59
   50.88   51.81   51.94   51.94   51.94   51.98   52.15   51.82   51.81   52.27
   52.26   52.24    51.8   51.94    52.1
  4553.6  4571.5  4574.5  4663.2  4666.1  4728.4  4741.3  4807.6  4858.6  4887.1
 4944.39  4944.5 4944.61  4947.5  4950.3 4950.41  4950.5  4950.7  4950.8  4959.9
  4963.9  4979.3  4986.9  4992.8  4995.8  4999.7  5002.2  5007.2  5011.6  5013.2
  5023.2  5033.9  5040.2  5041.1  5041.2  5050.2 5051.09  5051.2  5056.6  5066.4
  5070.5  5150.7 5174.99  5175.1 5175.21    5183  5214.6  5281.3  5282.7  5356.9
    5357  5358.1  5380.2  5398.2  5419.3
    50.8   50.55   50.51   51.49   51.52   51.55   51.54    51.5    51.8   51.96
    52.1   53.05   53.05   53.06   53.07   53.07   53.07   53.07   53.07   53.07
   53.06   53.06   53.05   53.05   53.05   53.05   53.05   53.04   53.04   53.04
   53.04   53.03   53.03   53.03   53.03   52.99   52.99   52.99   52.97   52.92
   52.91   52.57   52.47   52.47   51.95   51.99   52.16   51.83   51.82   52.28
   52.27   52.25   51.81   51.95    52.1
   50.71   50.45   50.41   51.39   51.42   51.45   51.44    51.4    51.7   51.86
      52      52      52   52.01   50.25   50.18   50.12   49.99   49.93    50.9
   49.77   49.77   49.76   49.76   49.76   49.76   49.76   49.75   49.75   49.75
   49.75   49.74   49.74   49.74   49.74    49.7    49.7   49.36   49.82    50.5
   50.79   51.72   51.85   51.85   51.85   51.89   52.06   51.73   51.72   52.18
   52.17   52.15   51.71   51.85   52.01
Pier Skew, UpSta & Num, DnSta & Num=  ,4979.3, 2 ,4979.3, 2 , 0 , 0 , 0 ,,
     1.7     1.7
   41.39   50.86
     1.7     1.7
    41.3   50.77
Pier Skew, UpSta & Num, DnSta & Num=  ,5013.2, 2 ,5013.2, 2 , 0 , 0 , 0 ,,
     1.7     1.7
   40.72   50.84
     1.7     1.7
   40.63   50.75
Abutment Skew #Up #Dn= , 2 , 2
  5050.2 5051.29
   49.36   49.79
  5050.2 5051.29
   49.27    49.7
BR Coef= 1 , 1 , 0 ,1.25, 0 ,,,0.8,0,2,0,
WSPro=,,,, 1 ,,,, 0 ,,,, 0 ,,,,-1 ,-1 ,-1 , 0 , 0 , 0 , 0 , 0
BR U #Sta/Elev= 55
  4553.6    50.8  4571.5   50.54  4574.5    50.5  4663.2   51.48  4666.1   51.51
  4728.4   51.54  4741.3   51.53  4807.6   51.49  4858.6   51.79  4887.1   51.95
 4944.39   52.09  4944.5   52.09 4944.61   52.09  4947.5    52.1  4950.3   50.34
 4950.41   50.27  4950.5   50.21  4950.7   50.08  4950.8   50.02  4959.9   50.99
  4963.9   49.13  4979.3   42.57  4986.9      41  4992.8   37.73  4995.8   36.19
  4999.7   36.33  5002.2   37.05  5007.2   37.81  5011.6   41.61  5013.2   41.85
  5023.2   42.37  5033.9   42.03  5040.2    48.5  5041.1   48.58  5041.2   48.59
  5050.2   49.36 5051.09   49.44  5051.2   49.45  5056.6   49.91  5066.4   50.59
  5070.5   50.88  5150.7   51.81 5174.99   51.94  5175.1   51.94 5175.21   51.94
    5183   51.98  5214.6   52.15  5281.3   51.82  5282.7   51.81  5356.9   52.27
    5357   52.26  5358.1   52.24  5380.2    51.8  5398.2   51.94  5419.3    52.1
BR U #Mann= 6
  4553.6      .2  4553.6     .06  4959.9     .04  5056.6     .06  5066.4      .1
  5419.3      .2
BR U Banks=4959.9,5056.6
BR D #Sta/Elev= 55
  4553.6   50.71  4571.5   50.45  4574.5   50.41  4663.2   51.39  4666.1   51.42
  4728.4   51.45  4741.3   51.44  4807.6    51.4  4858.6    51.7  4887.1   51.86
 4944.39      52  4944.5      52 4944.61      52  4947.5   52.01  4950.3   50.25
 4950.41   50.18  4950.5   50.12  4950.7   49.99  4950.8   49.93  4959.9    50.9
  4963.9   49.04  4979.3   42.48  4986.9   40.91  4992.8   37.64  4995.8    36.1
  4999.7   36.24  5002.2   36.96  5007.2   37.72  5011.6   41.52  5013.2   41.76
  5023.2   42.28  5033.9   41.94  5040.2   48.41  5041.1   48.49  5041.2    48.5
  5050.2   49.27 5051.09   49.35  5051.2   49.36  5056.6   49.82  5066.4    50.5
  5070.5   50.79  5150.7   51.72 5174.99   51.85  5175.1   51.85 5175.21   51.85
    5183   51.89  5214.6   52.06  5281.3   51.73  5282.7   51.72  5356.9   52.18
    5357   52.17  5358.1   52.15  5380.2   51.71  5398.2   51.85  5419.3   52.01
BR D #Mann= 6
  4553.6      .2  4553.6     .06  4959.9     .04  5056.6     .06  5066.4      .1
  5419.3      .2
BR D Banks=4959.9,5056.6
BC Design=,, 0 ,, 0 ,,,,,,
BC HTab HWMax=52.27
BC Use User HTab Curves=0
BC User HTab FreeFlow(D)= 0

Type RM Length L Ch R = 1 ,2935.5  ,195.8,191.5,187.9
BEGIN DESCRIPTION:
Downstream Section of Bridge/Culvert/Weir
END DESCRIPTION:
XS GIS Cut Line= 2
      3105574.77     13793266.35      3104710.13     13793223.53
#Sta/Elev= 30
  4553.6   50.72  4574.5   50.42  4666.1   51.43  4807.6   51.41  4887.1   51.87
  4947.5   52.02  4950.8   49.94  4959.9   50.91  4963.9   49.05  4979.3   42.49
  4986.9   40.92  4992.8   37.65  4995.8   36.11  4999.7   36.25  5002.2   36.97
  5007.2   37.73  5011.6   41.53  5013.2   41.77  5023.2   42.29  5033.9   41.95
  5040.2   48.42  5056.6   49.83  5066.4   50.51  5070.5    50.8  5150.7   51.73
  5214.6   52.07  5282.7   51.73  5356.9   52.19  5380.2   51.72  5419.3   52.02
#Mann= 6 , 1 , 0
  4553.6      .2       0  4553.6     .06       0  4959.9     .04       0
  5056.6     .06       0  5066.4      .1       0  5419.3      .2       0
#XS Ineff= 2 , 0
       0 4953.23   50.51 5063.27       0   51.81
Permanent Ineff=
       F       F
Bank Sta=4959.9,5056.6
XS Rating Curve= 0 ,0
Exp/Cntr=0.5,0.3