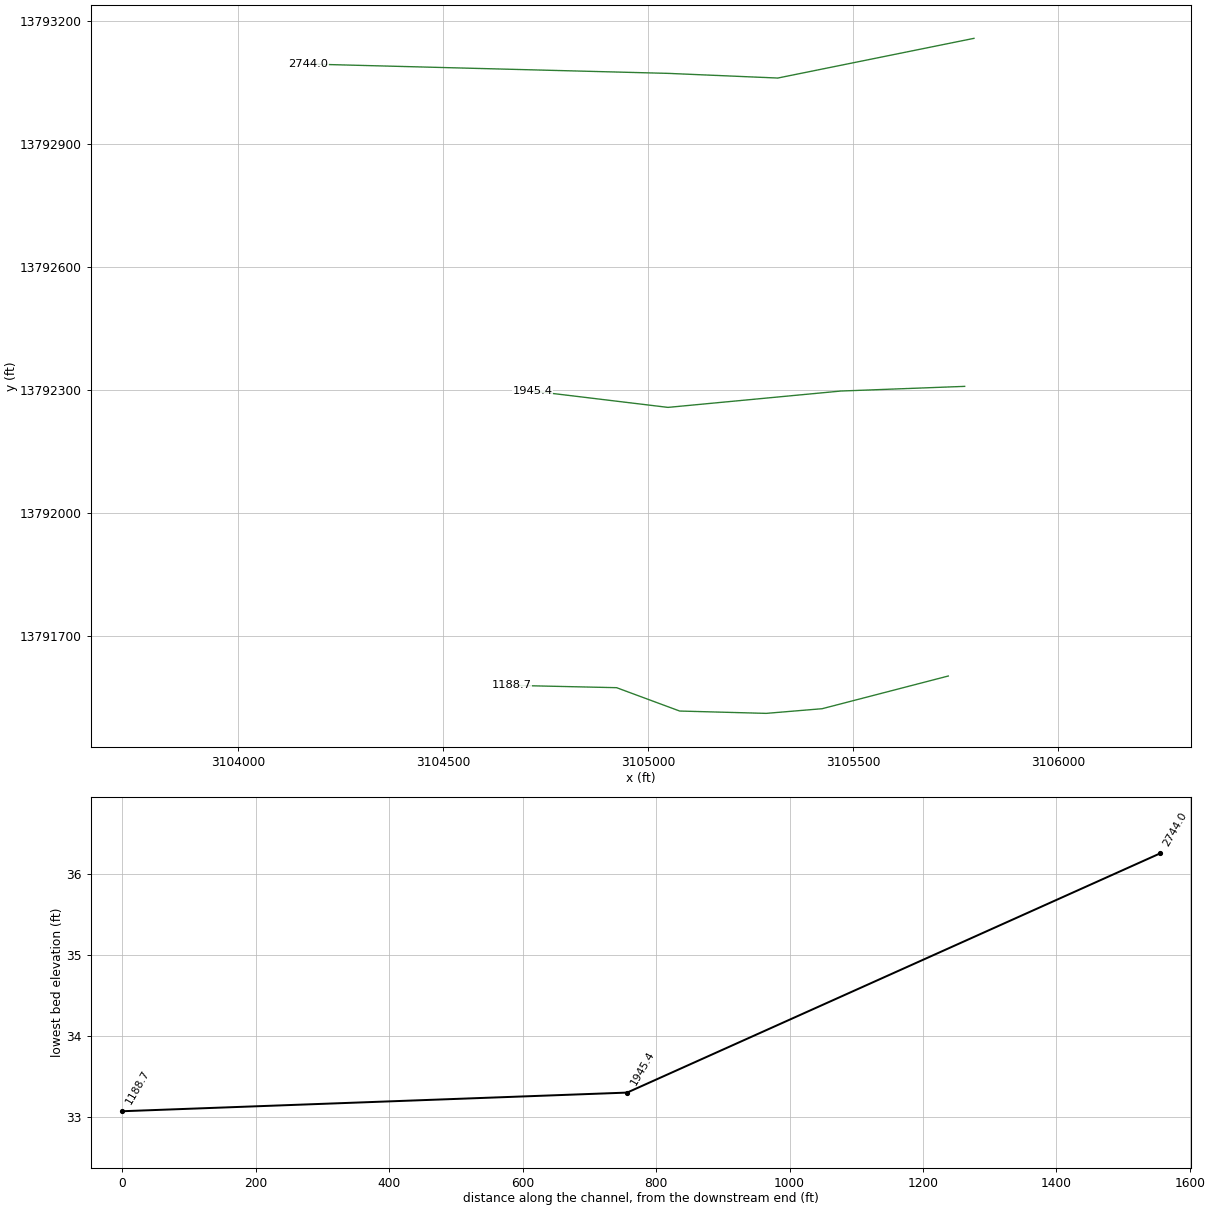
HEC-RAS study C161-00-00.PRJ: C161-00-00

--- C161-00-00.g01 (geometry) --- (continued)

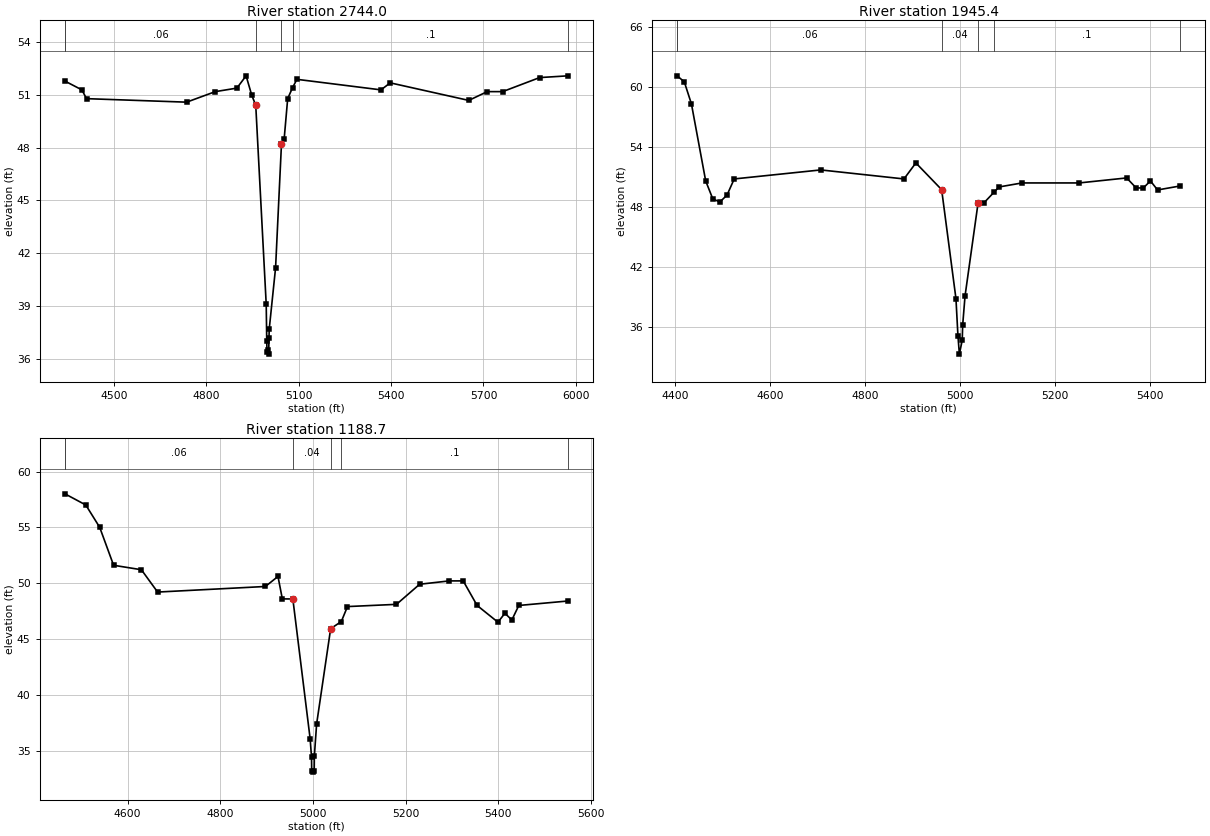
Type RM Length L Ch R = 1 ,2744.0  ,795.69,798.6,844.95
BEGIN DESCRIPTION:
Cross Section 2744.0
END DESCRIPTION:
XS GIS Cut Line= 4
      3105794.66     13793158.04      3105316.29     13793061.23
      3105048.63     13793072.62      3104171.62      13793095.4
#Sta/Elev= 29
  4341.2    51.8  4396.2    51.3  4411.2    50.8  4736.2    50.6  4829.3    51.2
  4899.3    51.4  4929.3    52.1  4947.9   50.98  4960.6   50.43  4994.6   39.09
  4996.3   37.02  4997.2   36.35  5000.2    36.5  5002.5   36.25  5003.6   37.17
  5004.4   37.68    5025   41.17  5044.2   48.24  5052.8   48.49  5064.3    50.8
  5080.2   51.43  5094.3    51.9  5367.2    51.3  5397.2    51.7  5652.2    50.7
  5712.2    51.2  5762.2    51.2  5882.2      52  5974.5    52.1
#Mann= 6 , 1 , 0
  4341.2      .2       0  4341.2     .06       0  4960.6     .04       0
  5044.2     .06       0  5080.2      .1       0  5974.5      .2       0
Bank Sta=4960.6,5044.2
XS Rating Curve= 0 ,0
Exp/Cntr=0.3,0.1

Type RM Length L Ch R = 1 ,1945.4  ,772.36,756.7,750.96
BEGIN DESCRIPTION:
Cross Section 1945.4
END DESCRIPTION:
XS GIS Cut Line= 4
      3105771.88      13792309.5      3105470.05     13792298.11
      3105048.63     13792258.25      3104718.33     13792298.11
#Sta/Elev= 30
    4405    61.1    4420    60.5    4435    58.3    4465    50.6    4480    48.8
    4495    48.5    4510    49.2    4525    50.8    4707    51.7    4882    50.8
    4907    52.4  4961.2   49.73  4991.3   38.84  4995.5   35.11  4998.5    33.3
  5004.5   34.69  5005.4   36.18  5010.4   39.11  5037.7   48.36  5049.7   48.39
  5071.3   49.47    5082      50  5130.3    50.4  5250.3    50.4  5350.3    50.9
  5370.3    49.9  5385.3    49.9  5400.3    50.6  5415.3    49.7    5463    50.1
#Mann= 6 , 1 , 0
    4405      .2       0    4405     .06       0  4961.2     .04       0
  5037.7     .06       0  5071.3      .1       0    5463      .2       0
Bank Sta=4961.2,5037.7
XS Rating Curve= 0 ,0
Exp/Cntr=0.3,0.1

Type RM Length L Ch R = 1 ,1188.7  ,0,0,0
BEGIN DESCRIPTION:
Cross Section 1188.7
END DESCRIPTION:
XS GIS Cut Line= 6
      3105732.02     13791603.34      3105424.49     13791523.61
      3105287.82     13791512.22      3105077.11     13791517.91
      3104923.34     13791574.86      3104667.07     13791580.56
#Sta/Elev= 30
  4464.7      58  4509.7      57  4539.7      55  4569.7    51.6  4629.7    51.2
  4664.7    49.2  4897.4    49.7  4924.5    50.6  4933.9   48.59  4956.6   48.58
  4993.9   36.07  4996.9   34.42  4997.3   33.15    5000   33.07  5002.7   33.18
    5003    34.5  5007.9   37.38  5038.2   45.92  5061.2   46.56  5074.5    47.9
  5180.3    48.1  5230.3    49.9  5294.3    50.2  5324.3    50.2  5354.3      48
  5399.3    46.5  5414.3    47.3  5429.3    46.7  5444.3      48  5550.6    48.4
#Mann= 6 , 1 , 0
  4464.7      .2       0  4464.7     .06       0  4956.6     .04       0
  5038.2     .06       0  5061.2      .1       0  5550.6      .2       0
Bank Sta=4956.6,5038.2
XS Rating Curve= 0 ,0
Exp/Cntr=0.3,0.1

Chan Stop Cuts=-1
Use User Specified Reach Order=0
Composite Channel Slope=5